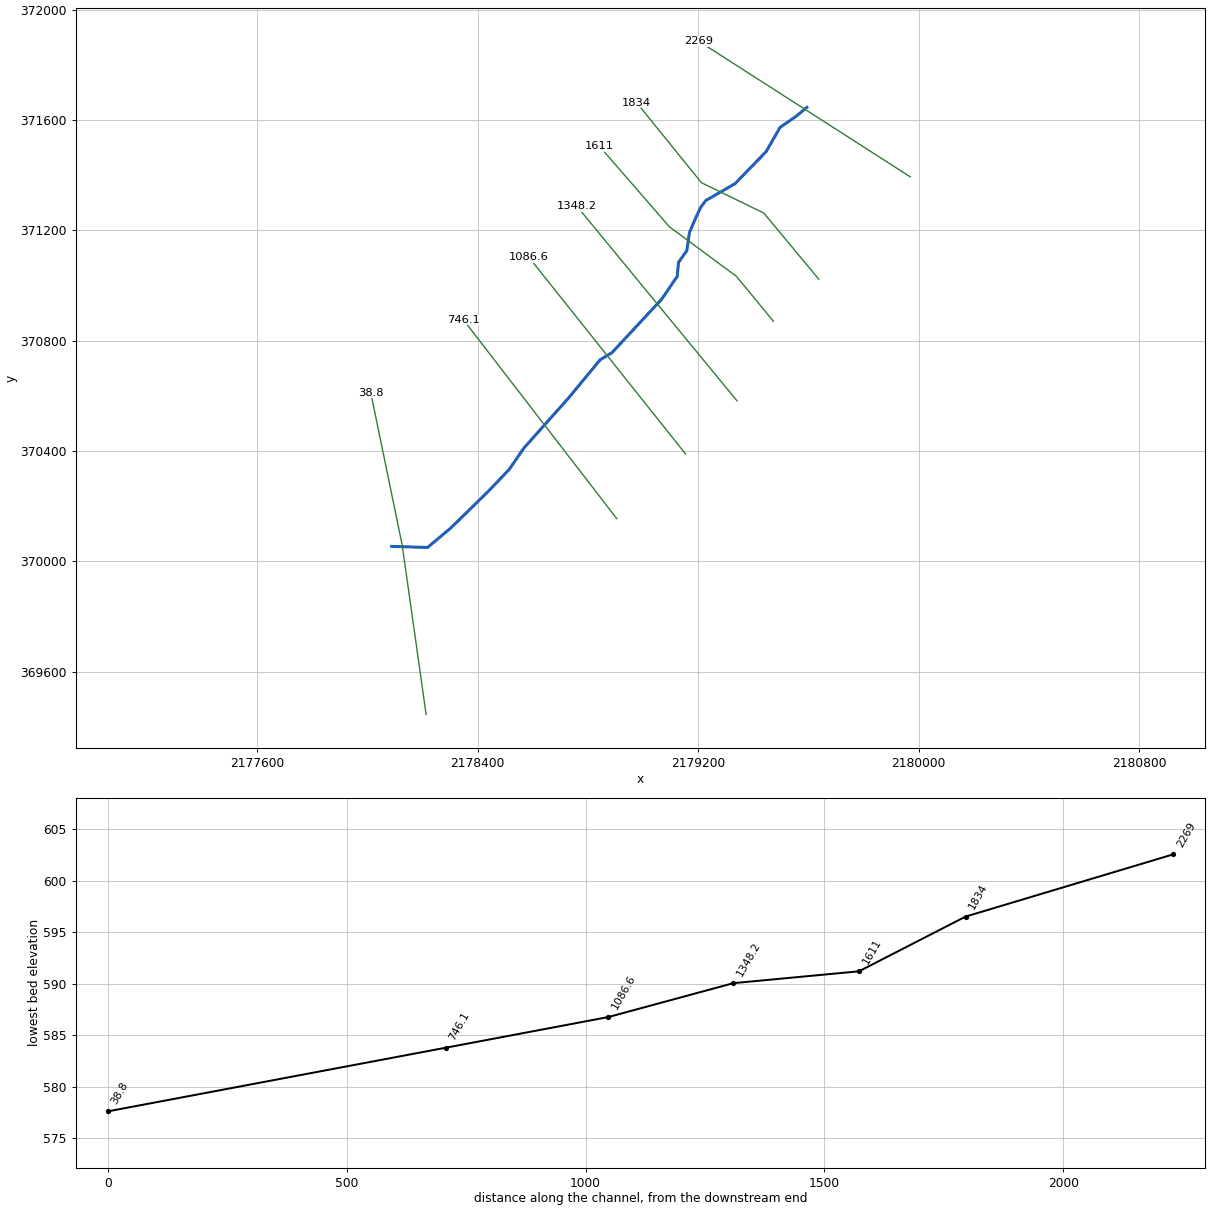
--- NP125.prj (project) ---

Proj Title=NP125
Current Plan=p01
Geom File=g01
Flow File=f01
Plan File=p01
DSS Export Rating Curves=0
DSS Export Rating Curve Sorted=0
DSS Export Volume Flow Curves=0
DXF OffsetX=0
DXF OffsetY=0
DXF ScaleX=0
DXF ScaleY=0

--- NP125.p01 (plan) ---

Plan Title=Floodplain
Program Version=4.00
Geom File=g01
Flow File=f01
K Sum by GR=0
Std Step Tol=0.01
Critical Tol=0.01
Num of Std Step Trials=20
Max Error Tol=0.3
Flow Tol Ratio=0.001
Split Flow NTrial=30
Split Flow Tol=0.02
Split Flow Ratio=0.02
Log Output Level=0
Friction Slope Method=1
Unsteady Friction Slope Method=2
Unsteady Bridges Friction Slope Method=1
Global Log Level=0
CheckData=False
Run HTab=0
Run UNet=0
Run PostProcess=0
UNET Theta=0
UNET Theta Warmup=0
UNET ZTol=0
UNET ZSATol=0
UNET MxIter=0
UNET MaxInSteps=0
UNET DtIC=0
UNET DtMin=0
UNET MaxCRTS=0
UNET WFStab=0
UNET SFStab=0
UNET WFX=0
UNET SFX=0
UNET DSS MLevel=0
UNET DZMax Abort=0
UNET Convert EG Bridges=0
UNET Use Existing IB Tables=0
UNET Froude Limit=0
UNET Froude Power=0
Write IC File=0
Echo Input=False
Echo Output=False
Write Detailed=0

--- NP125.f01 (steady flow) ---

Flow Title=NFF Regression Equation
Program Version=4.00
Number of Profiles=1
Profile Names=P100yr
River Rch & RM=NP125,Main      ,2269
     761
River Rch & RM=NP125,Main      ,38.8
     793
Boundary for River Rch & Prof#=NP125,Main      ,1
Up Type=0
Dn Type=3
Dn Slope=0.010016

--- NP125.g01 (geometry) ---

Geom Title=USGS 10m DEM
Program Version=4.00

River Reach=NP125     ,Main
Reach XY= 23
     2179594.038      371645.511     2179556.841      371614.365
     2179496.746      371572.770     2179446.539      371485.217
     2179358.101      371394.110     2179333.483      371368.747
     2179227.530      371307.842     2179209.057      371282.898
     2179190.697      371244.276     2179168.288      371192.004
     2179158.761      371126.223     2179128.519      371083.228
     2179123.972      371032.814     2179067.762      370950.280
     2178887.335      370756.315     2178844.134      370730.250
     2178729.647      370591.606     2178568.728      370411.483
     2178514.142      370332.444     2178439.070      370253.968
     2178304.046      370121.873     2178218.703      370050.152
     2178088.699      370054.038

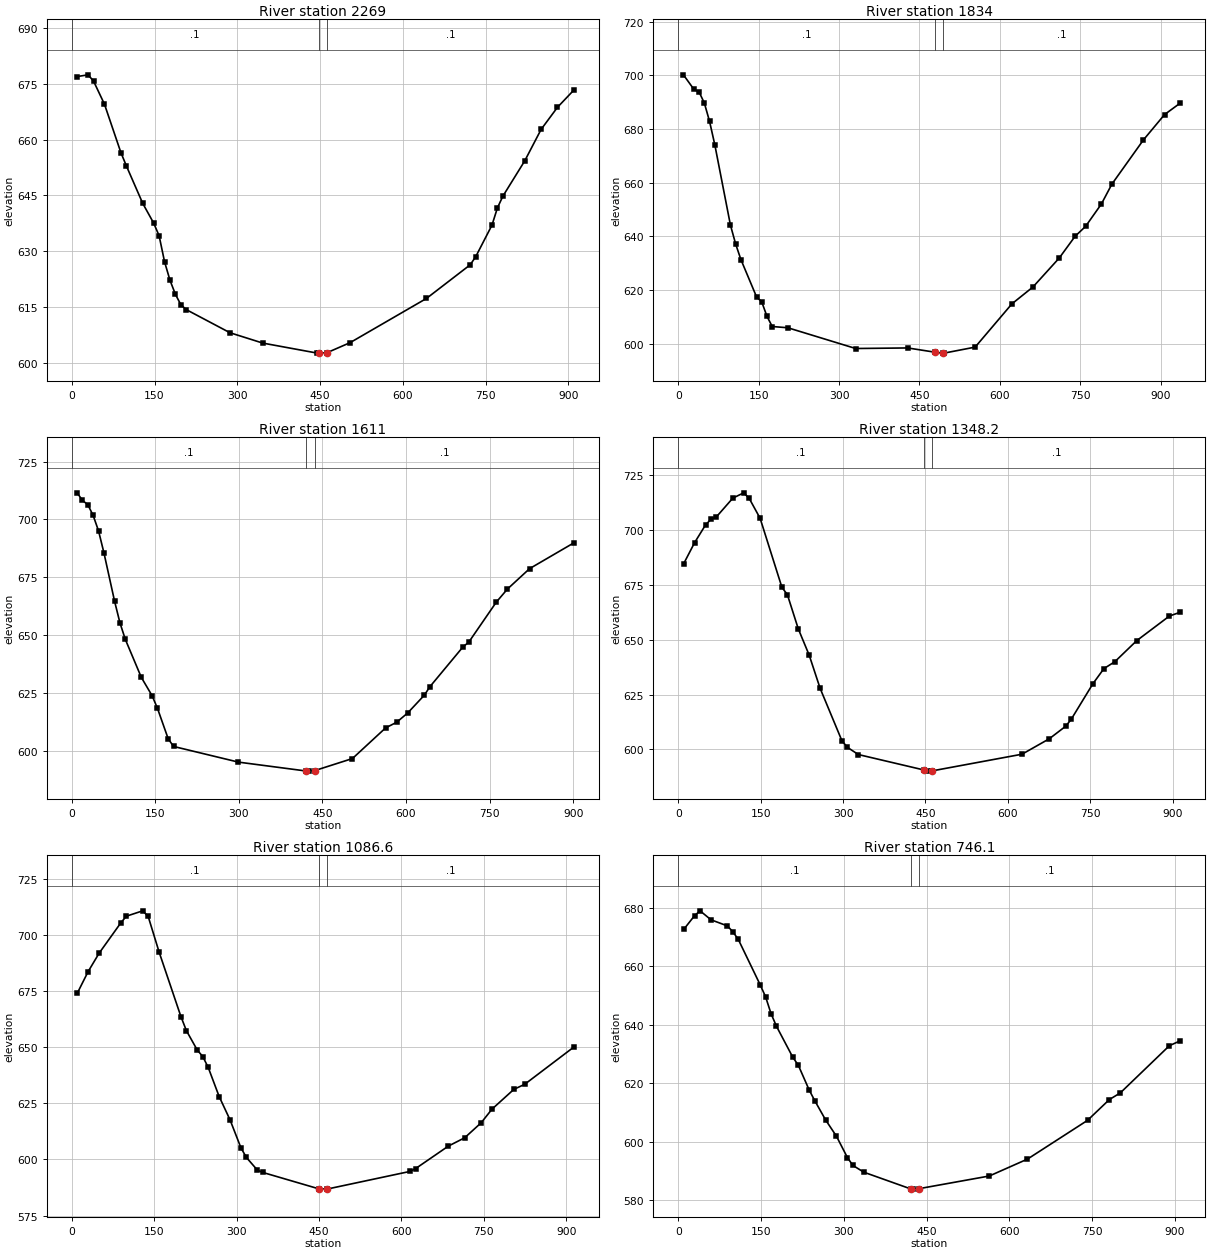
Type RM Length L Ch R = 1 ,2269,430.7,435.1,439.4
XS GIS Cut Line= 3
     2179969.384      371393.479     2179586.371      371639.091
     2179203.356      371884.703
#Sta/Elev= 30
     9.9  676.97    29.7  677.43    39.6  675.70    59.3  669.51    89.0  656.53
    98.9  652.96   128.6  642.86   148.4  637.56   158.3  634.15   168.2  627.13
   178.0  622.18   187.9  618.38   197.8  615.58   207.7  614.27   286.8  608.06
   346.2  605.28   445.1  602.58   447.5  602.58   462.5  602.69   504.5  605.40
   642.9  617.29   722.1  626.33   732.0  628.48   761.6  637.00   771.5  641.65
   781.4  644.80   821.0  654.29   850.7  662.76   880.3  668.69   910.0  673.33
#Mann= 3 , 0 , 0
       0     0.1       0   447.5   0.045       0   462.5     0.1       0
Bank Sta=   447.5,   462.5
Exp/Cntr=0.3,0.1

Type RM Length L Ch R = 1 ,1834,229.7,222.9,216.2
XS GIS Cut Line= 4
     2179637.297      371022.632     2179437.928      371262.321
     2179211.472      371372.787     2178976.731      371662.762
#Sta/Elev= 30
     9.7  700.16    29.2  694.76    39.0  693.73    48.7  689.66    58.5  682.79
    68.2  674.15    97.4  644.20   107.2  637.11   116.9  631.39   146.1  617.49
   155.9  615.56   165.6  610.21   175.4  606.44   204.6  605.97   331.1  598.25
   428.1  598.46   478.6  596.89   493.6  596.56   495.9  596.53   554.0  598.77
   622.6  614.88   661.9  621.17   711.0  631.97   740.5  640.04   760.1  643.74
   789.5  652.05   809.2  659.48   868.1  675.96   907.4  685.36   936.8  689.66
#Mann= 3 , 0 , 0
       0     0.1       0   478.6   0.045       0   493.6     0.1       0
Bank Sta=   478.6,   493.6
Exp/Cntr=0.3,0.1

Type RM Length L Ch R = 1 ,1611,267.6,262.8,258.1
XS GIS Cut Line= 4
     2179472.937      370869.888     2179338.555      371033.141
     2179095.482      371212.611     2178841.410      371505.347
#Sta/Elev= 30
     9.6  711.47    19.2  708.20    28.8  706.35    38.4  701.68    48.1  694.99
    57.7  685.57    76.9  664.57    86.5  655.26    96.1  648.16   124.9  631.69
   144.2  623.81   153.8  618.37   173.0  605.25   182.6  601.89   299.2  595.11
     421  591.26   425.9  591.22     436  591.44   503.8  596.66   563.3  609.89
   583.2  612.34   603.0  616.36   632.9  624.05   642.8  627.69   702.4  644.96
   712.4  646.88   762.1  664.27   781.9  669.87   821.7  678.70   901.2  689.85
#Mann= 3 , 0 , 0
       0     0.1       0     421   0.045       0     436     0.1       0
Bank Sta=     421,     436
Exp/Cntr=0.3,0.1

Type RM Length L Ch R = 1 ,1348.2,262,261.6,261.2
XS GIS Cut Line= 2
     2179341.141      370581.361     2178760.135      371287.195
#Sta/Elev= 30
     9.9  684.73    29.8  694.35    49.7  702.42    59.6  705.03    69.6  706.14
    99.4  714.66   119.2  717.08   129.2  714.56   149.1  705.44   188.8  673.93
   198.7  670.63   218.6  654.99   238.5  642.96   258.4  627.82   298.1  603.90
   308.0  600.94   327.9  597.64   447.9  590.56   457.1  590.07   462.9  590.21
   626.0  597.79   675.7  604.85   705.5  610.56   715.5  613.70   755.2  630.02
   775.1  636.86   795.0  640.01   834.7  649.59   894.3  660.84   914.2  662.61
#Mann= 3 , 0 , 0
       0     0.1       0   447.9   0.045       0   462.9     0.1       0
Bank Sta=   447.9,   462.9
Exp/Cntr=0.3,0.1

Type RM Length L Ch R = 1 ,1086.6,340.9,340.5,340.2
XS GIS Cut Line= 2
     2179154.570      370388.654     2178585.160      371103.266
#Sta/Elev= 30
     9.9  674.06    29.8  683.77    49.7  691.94    89.4  705.53    99.3  708.45
   129.1  710.85   139.0  708.39   158.9  692.50   198.6  663.73   208.6  657.43
   228.4  648.77   238.4  645.89   248.3  641.04   268.2  628.06   288.0  617.68
   307.9  605.16   317.8  600.90   337.7  595.28   347.6  594.22   449.2  586.94
   464.2  586.78   615.8  594.69   625.7  595.93   685.3  605.96   715.1  609.68
   744.9  616.33   764.8  622.45   804.5  631.25   824.3  633.52   913.7  650.12
#Mann= 3 , 0 , 0
       0     0.1       0   449.2   0.045       0   464.2     0.1       0
Bank Sta=   449.2,   464.2
Exp/Cntr=0.3,0.1

Type RM Length L Ch R = 1 ,746.1,719.6,707.3,696.2
XS GIS Cut Line= 3
     2178904.746      370154.596     2178626.798      370514.833
     2178348.851      370875.069
#Sta/Elev= 30
     9.9  672.66    29.7  677.40    39.6  679.03    59.3  675.97    89.0  673.88
    98.9  671.89   108.8  669.26   148.4  653.76   158.3  649.62   168.2  643.85
   178.0  639.54   207.7  628.91   217.6  626.20   237.4  617.69   247.3  614.12
   267.1  607.48   286.8  601.89   306.6  594.61   316.5  591.92   336.3  589.60
   421.5  583.87   425.3  583.80   436.5  583.96   563.8  588.29   633.0  594.08
   741.8  607.33   781.4  614.45   801.2  616.72   890.2  632.88   910.0  634.57
#Mann= 3 , 0 , 0
       0     0.1       0   421.5   0.045       0   436.5     0.1       0
Bank Sta=   421.5,   436.5
Exp/Cntr=0.3,0.1

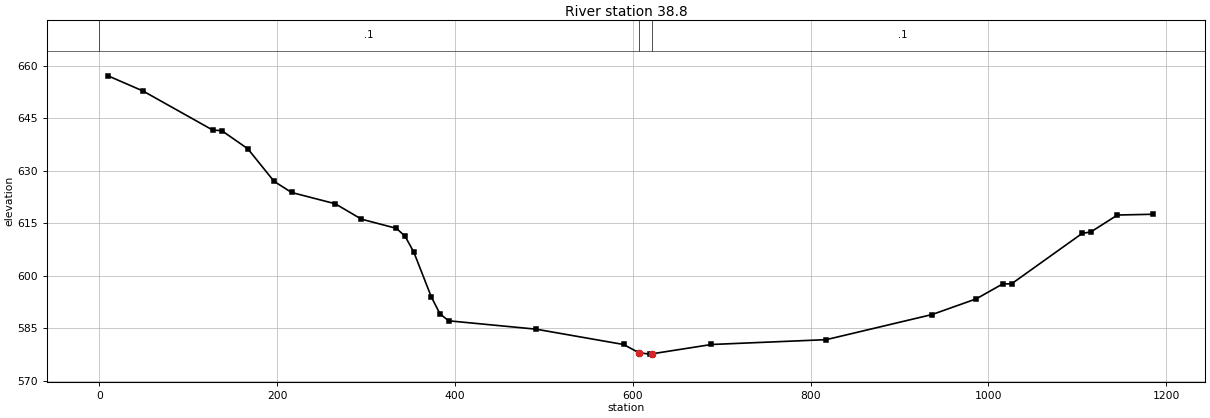
Type RM Length L Ch R = 1 ,38.8,42.6,38.8,33.7
XS GIS Cut Line= 3
     2178213.368      369444.548     2178126.792      370057.501
     2178012.513      370611.583
#Sta/Elev= 30
     9.8  657.07    49.1  652.74   127.7  641.56   137.6  641.43   167.0  636.24
   196.5  626.95   216.2  623.77   265.3  620.55   294.8  616.15   334.1  613.53
   343.9  611.27   353.7  606.74   373.4  593.94   383.2  589.08   393.0  587.13
   491.3  584.74   589.6  580.37   606.9  578.02   619.0  577.62   621.9  577.72
   688.5  580.37   817.5  581.75   936.6  588.92   986.3  593.40  1016.1  597.67
  1026.0  597.69  1105.4  612.08  1115.3  612.52  1145.1  617.33  1184.8  617.55
#Mann= 3 , 0 , 0
       0     0.1       0   606.9   0.045       0   621.9     0.1       0
Bank Sta=   606.9,   621.9
Exp/Cntr=0.3,0.1